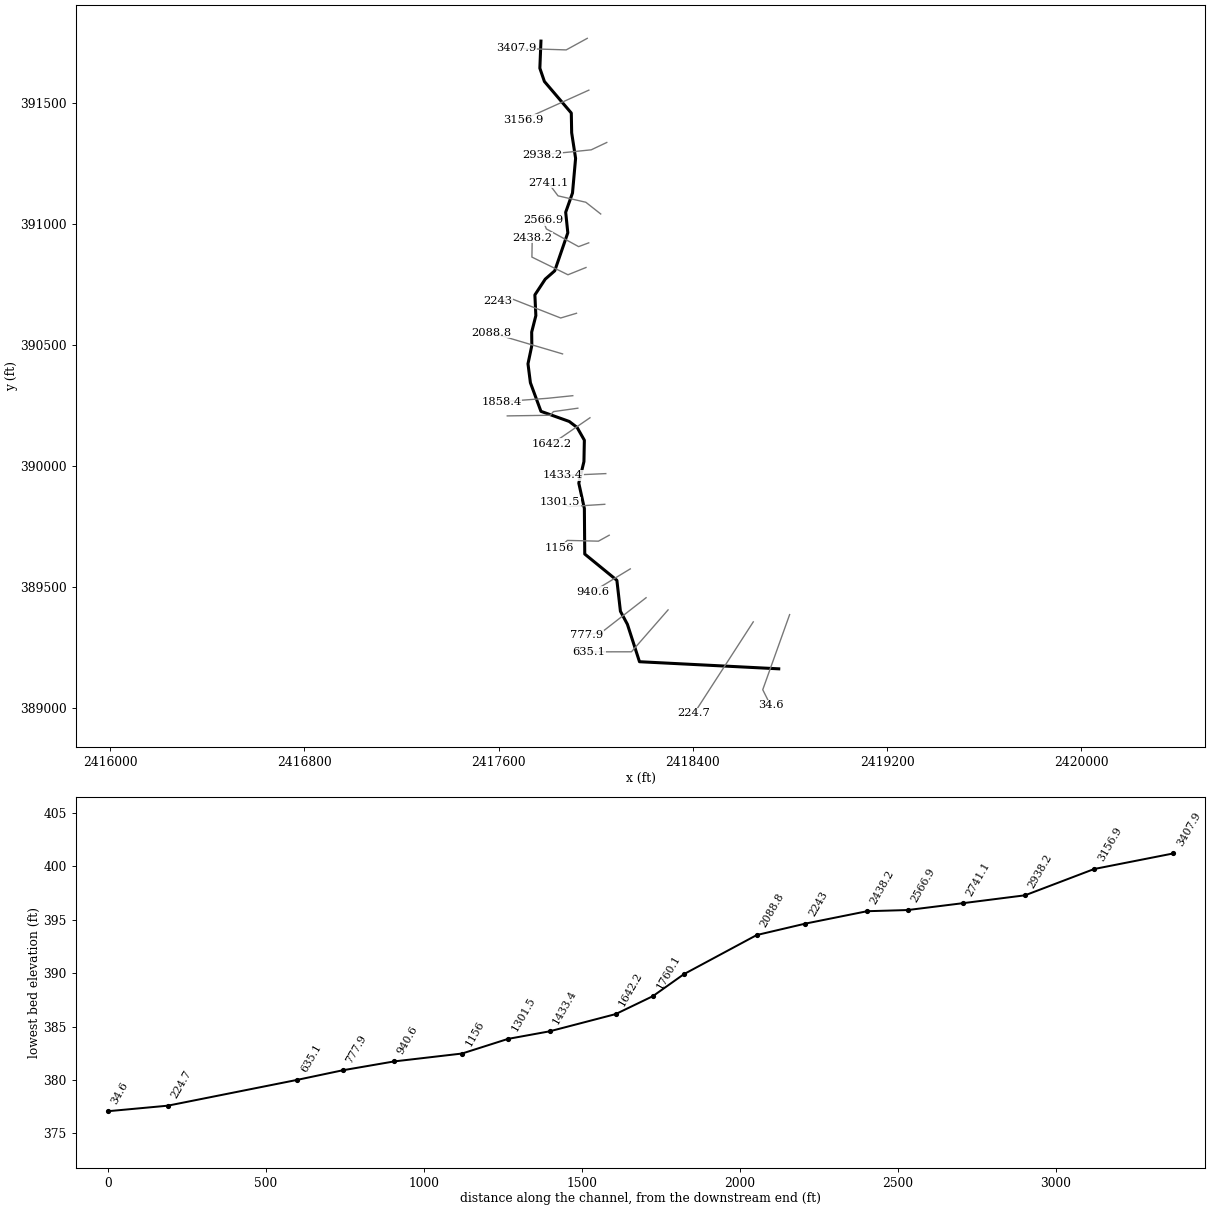
--- TRIB1PTMC.prj (project) ---

Proj Title=TRIB1PTMC
Current Plan=p01
Default Exp/Contr=0,0
English Units
Geom File=g01
Flow File=f01
Plan File=p01
BEGIN DESCRIPTION:
END DESCRIPTION:
DSS Export Rating Curves= 0
DSS Export Rating Curve Sorted= 0
DSS Export Volume Flow Curves= 0
DXF OffsetX= 0
DXF OffsetY= 0
DXF ScaleX= 0
DXF ScaleY= 0

--- TRIB1PTMC.p01 (plan) ---

Plan Title=Floodplain
Program Version=4.00
Geom File=g01
Flow File=f01
K Sum by GR=0
Std Step Tol=0.01
Critical Tol=0.01
Num of Std Step Trials=20
Max Error Tol=0.3
Flow Tol Ratio=0.001
Split Flow NTrial=30
Split Flow Tol=0.02
Split Flow Ratio=0.02
Log Output Level=0
Friction Slope Method=1
Unsteady Friction Slope Method=2
Unsteady Bridges Friction Slope Method=1
Global Log Level=0
CheckData=False
Run HTab=0
Run UNet=0
Run PostProcess=0
UNET Theta=0
UNET Theta Warmup=0
UNET ZTol=0
UNET ZSATol=0
UNET MxIter=0
UNET MaxInSteps=0
UNET DtIC=0
UNET DtMin=0
UNET MaxCRTS=0
UNET WFStab=0
UNET SFStab=0
UNET WFX=0
UNET SFX=0
UNET DSS MLevel=0
UNET DZMax Abort=0
UNET Convert EG Bridges=0
UNET Use Existing IB Tables=0
UNET Froude Limit=0
UNET Froude Power=0
Write IC File=0
Echo Input=False
Echo Output=False
Write Detailed=0

--- TRIB1PTMC.f01 (steady flow) ---

Flow Title=NFF Regression Equation
Program Version=4.00
Number of Profiles=1
Profile Names=P100yr
River Rch & RM=TRIB1PTMC,Main      ,3407.9
552.1641
River Rch & RM=TRIB1PTMC,Main      ,2741.1
563.6503
River Rch & RM=TRIB1PTMC,Main      ,940.6
622.7635
River Rch & RM=TRIB1PTMC,Main      ,635.1
623.6820
Boundary for River Rch & Prof#=TRIB1PTMC,Main      ,1
Up Type=0
Dn Type=3
Dn Slope=0.003724

--- TRIB1PTMC.g01 (geometry) ---

Geom Title=USGS 10m DEM
Program Version=4.10

River Reach=TRIB1PTMC       ,Main
Reach XY= 30
     2417774.575      391753.655     2417770.095      391641.652
     2417788.818      391587.071     2417899.575       391456.78
     2417901.114      391375.205      2417917.26      391269.736
     2417904.501      391126.772     2417876.448      391047.415
     2417885.215      390962.684     2417831.375      390805.778
     2417792.312      390771.403     2417749.604      390706.299
     2417753.609      390620.777      2417736.43      390552.855
     2417737.008      390497.225     2417721.228      390422.074
     2417731.173      390343.933     2417774.575      390225.877
     2417890.895       390184.21     2417923.506      390159.364
      2417953.35      390106.707     2417951.614      390018.661
     2417930.433      389929.623     2417953.395      389824.835
     2417954.966      389636.993     2418087.257       389528.66
     2418101.869      389400.834     2418130.602      389347.097
     2418180.332      389192.699     2418753.742      389163.377

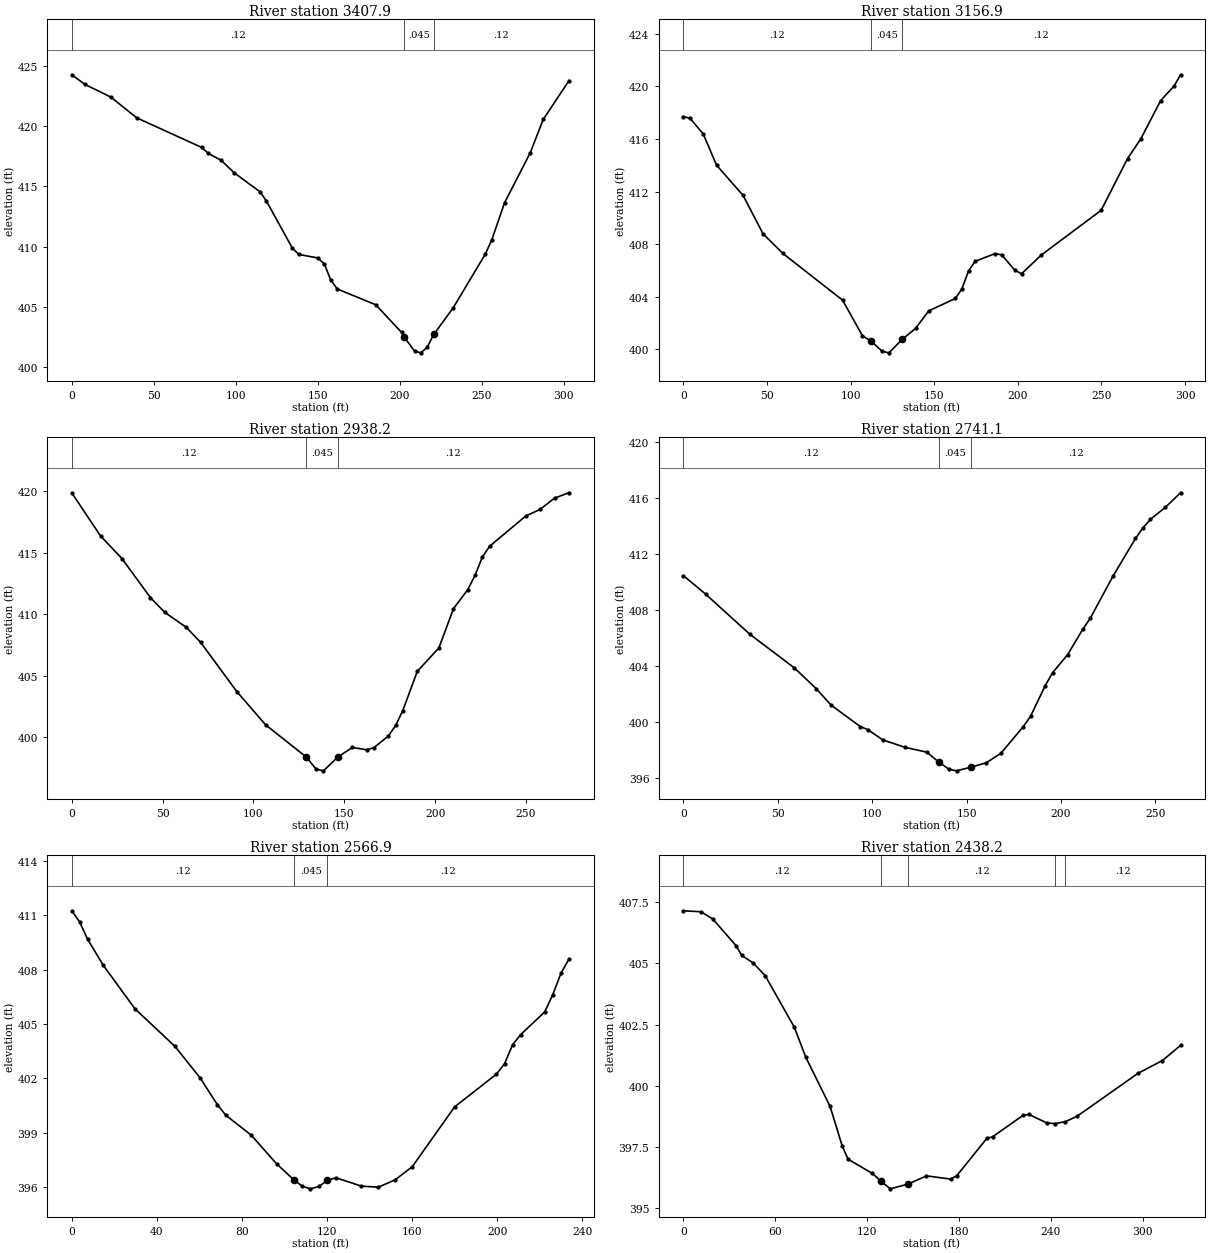
Type RM Length L Ch R = 1 ,3407.9  ,240.6,250.9,260
XS GIS Cut Line= 3
      2417965.35      391765.037     2417878.544      391717.293
     2417674.551      391723.804
#Sta/Elev= 30
       0  424.24     7.9  423.45    23.8  422.39    39.6  420.67    79.2  418.22
    83.2  417.73    91.1  417.15    99.1  416.11   114.8  414.54   118.7  413.77
   134.4   409.9   138.3  409.36   150.1  409.06     154  408.57   157.9  407.23
   161.9  406.49   185.4  405.18   201.1  402.89   202.7  402.51     209  401.35
   212.9   401.2   216.8  401.68   220.7  402.72   232.5  404.91   252.1  409.36
   256.1  410.55   263.9  413.63   279.6  417.78   287.5  420.54   303.2  423.75
#Mann= 3 ,-1 , 0
       0     .12       0   202.7    .045       0   220.7     .12       0
Bank Sta=202.7,220.7
XS Rating Curve= 0 ,0
Exp/Cntr=0.3,0.1

Type RM Length L Ch R = 1 ,3156.9  ,225.7,218.7,212.1
XS GIS Cut Line= 2
      2417971.86      391551.278      2417700.94      391428.752
#Sta/Elev= 30
       0  417.69       4  417.56    11.9  416.36    19.8     414    35.7   411.7
    47.6  408.79    59.5  407.29    95.2  403.74     107  401.05   112.2  400.62
   118.9  399.86   122.9  399.74   130.8  400.76   138.8  401.59   146.7  402.93
   162.6  403.87   166.5  404.59   170.5  405.96   174.4  406.69   186.3  407.28
   190.3  407.19   198.2  406.02   202.2  405.75   214.1  407.18   249.8  410.57
   265.6   414.5   273.6  416.02   285.4  418.91   293.4  420.01   297.3  420.87
#Mann= 3 ,-1 , 0
       0     .12       0   112.2    .045       0   130.8     .12       0
Bank Sta=112.2,130.8
XS Rating Curve= 0 ,0
Exp/Cntr=0.3,0.1

Type RM Length L Ch R = 1 ,2938.2  ,204.5,197.2,189.6
XS GIS Cut Line= 3
     2418045.645      391335.349     2417981.626      391304.967
     2417779.803      391284.351
#Sta/Elev= 30
       0  419.87    15.8  416.38    27.6  414.54    43.3  411.36    51.2  410.16
      63  408.95    70.9  407.73    90.8  403.73   106.7  401.02  129.01  398.41
   134.5  397.42   138.5  397.28   146.4  398.39   154.4  399.18   162.4  398.99
   166.3  399.16   174.3  400.12   178.3  400.97   182.2  402.18   190.2  405.37
   202.1  407.28   210.1  410.46     218  412.02     222  413.18     226  414.66
     230  415.54   249.9     418   257.8  418.54   265.8  419.46   273.7  419.89
#Mann= 3 ,-1 , 0
       0     .12       0  129.01    .045       0   146.4     .12       0
Bank Sta=129.01,146.4
XS Rating Curve= 0 ,0
Exp/Cntr=0.3,0.1

Type RM Length L Ch R = 1 ,2741.1  ,179.8,174.1,167.4
XS GIS Cut Line= 4
     2418020.688       391040.21      2417959.36      391088.648
     2417844.907       391115.08     2417804.239       391169.29
#Sta/Elev= 30
       0  410.46    11.7  409.15    35.2  406.28    58.6   403.9    70.3  402.41
    78.2  401.23    93.8  399.69    97.7  399.48   105.6  398.75   117.3  398.22
     129  397.87   135.5  397.14   140.8  396.65   144.7  396.54   152.5  396.81
   160.4  397.11   168.2  397.79     180  399.68   183.9  400.42   191.7  402.62
   195.6  403.54   203.6  404.83   211.6  406.64   215.6  407.43   227.5   410.4
   239.5  413.11   243.4  413.86   247.4  414.47   255.4  415.34   263.4  416.37
#Mann= 3 ,-1 , 0
       0     .12       0   135.5    .045       0   152.5     .12       0
Bank Sta=135.5,152.5
XS Rating Curve= 0 ,0
Exp/Cntr=0.3,0.1

Type RM Length L Ch R = 1 ,2566.9  ,127.2,128.7,129.3
XS GIS Cut Line= 4
     2417971.339      390921.156     2417929.673      390905.531
     2417797.034      390978.622     2417782.537      391013.604
#Sta/Elev= 30
       0  411.24     3.7  410.62     7.4  409.67    14.8  408.23    29.7  405.83
    48.5  403.76    60.4  402.01    68.4  400.55    72.4  399.96    84.4  398.86
    96.3  397.28   104.3  396.41   108.3  396.05   112.2   395.9   116.2  396.03
   120.2  396.37   124.2  396.51   136.2  396.05   144.1  395.99   152.1   396.4
   160.1  397.12     180  400.42   199.7  402.23   203.5   402.8   207.3  403.85
   211.1  404.41   222.4  405.66   226.2  406.62     230  407.78   233.8  408.58
#Mann= 3 ,-1 , 0
       0     .12       0   104.3    .045       0   120.2     .12       0
Bank Sta=104.3,120.2
XS Rating Curve= 0 ,0
Exp/Cntr=0.3,0.1

Type RM Length L Ch R = 1 ,2438.2  ,193.8,195.3,195.9
XS GIS Cut Line= 4
     2417960.055      390819.377     2417885.836      390789.429
     2417737.398      390862.346       2417738.7      390941.773
#Sta/Elev= 30
       0  407.15    11.4  407.11    19.1  406.82    34.3  405.73    38.1  405.33
    45.7  405.01    53.4   404.5    72.4   402.4      80  401.16    95.8  399.16
   103.7  397.55   107.6     397   123.4  396.42   129.3  396.09   135.2  395.79
     147  395.99   158.8  396.32   174.5  396.19   178.5  396.32   198.2  397.85
   202.1  397.92   221.8  398.79   225.7  398.83   237.5  398.48   242.9398.4556
  249.59398.5352   257.3  398.76     297  400.51   312.9  401.03   324.8  401.65
#Mann= 5 ,-1 , 0
       0     .12       0   129.3    .045       0     147     .12       0
   242.9     .06       0  249.59     .12       0
Bank Sta=129.3,147
XS Rating Curve= 0 ,0
Exp/Cntr=0.3,0.1

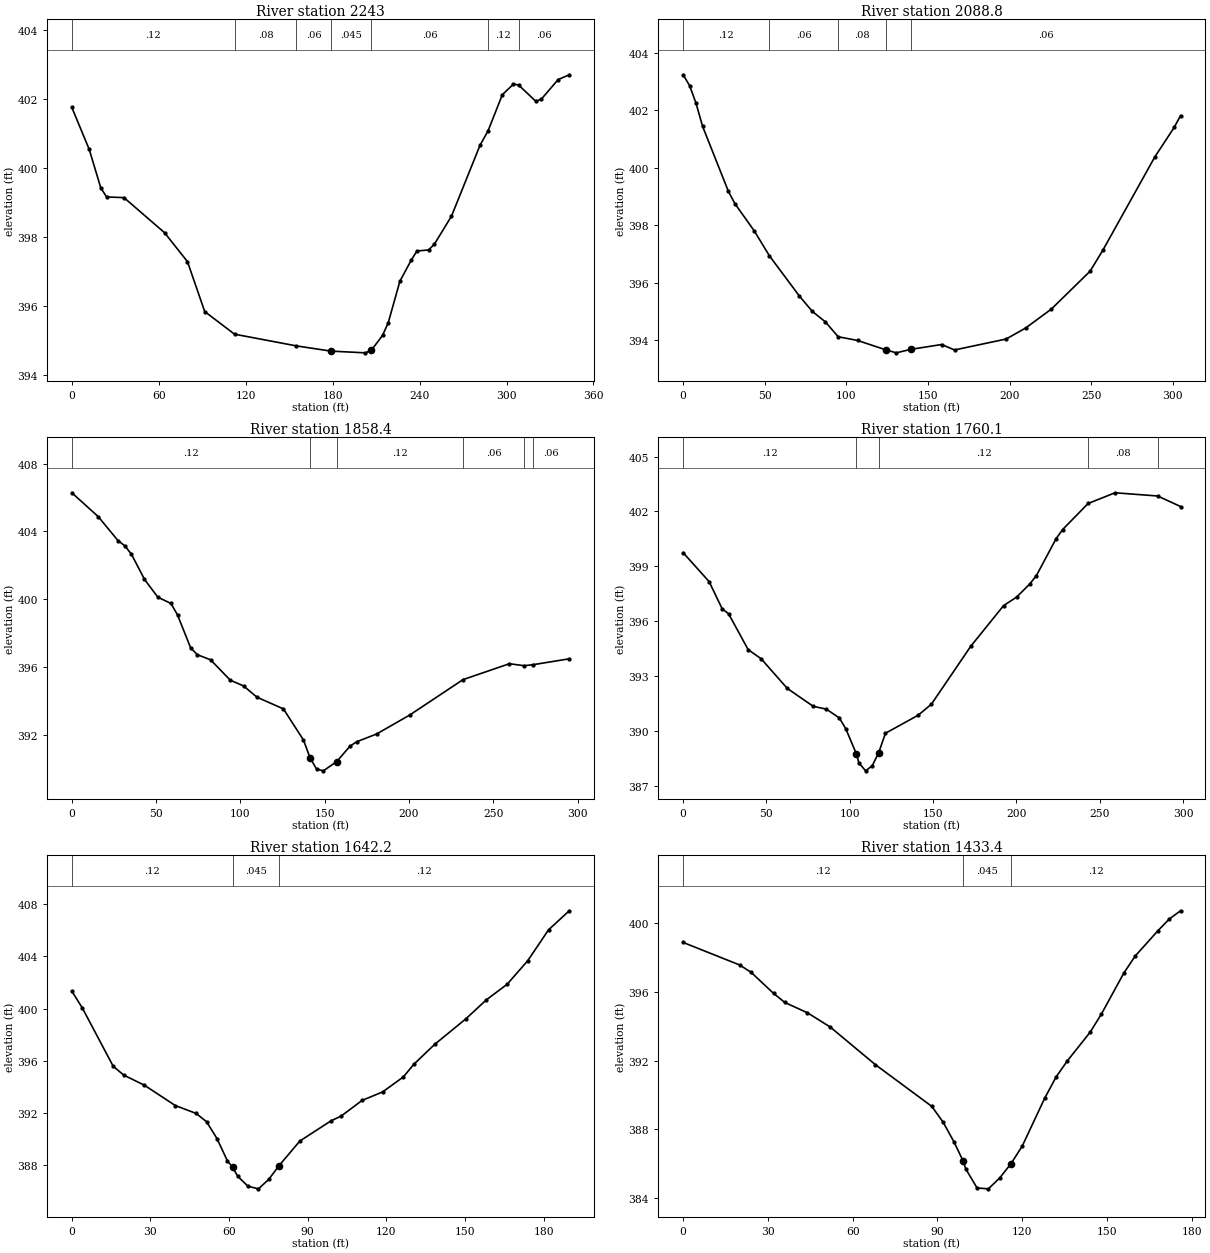
Type RM Length L Ch R = 1 ,2243    ,151.5,154.1,155.8
XS GIS Cut Line= 4
     2417920.992      390630.575     2417855.888      390611.043
     2417660.575      390687.866     2417595.471      390681.356
#Sta/Elev= 30
       0  401.76      12  400.54      20  399.42      24  399.16      36  399.14
      64  398.12    79.8  397.28    91.7  395.83  112.26395.1724  154.88394.8327
   178.8  394.68   202.6  394.63   206.6   394.7   214.5  395.14   218.4  395.51
   226.4  396.71   234.3  397.33   238.2  397.59   246.2  397.62   250.1  397.78
     262   398.6   281.7  400.66  287.35401.0896   297.1  402.13   304.8  402.44
  308.32402.4122   320.2  401.94     324     402   335.6  402.57   343.3  402.71
#Mann= 7 ,-1 , 0
       0     .12       0  112.26     .08       0  154.88     .06       0
   178.8    .045       0   206.6     .06       0  287.35     .12       0
  308.32     .06       0
Bank Sta=178.8,206.6
XS Rating Curve= 0 ,0
Exp/Cntr=0.3,0.1

Type RM Length L Ch R = 1 ,2088.8  ,222,230.4,239.1
XS GIS Cut Line= 2
     2417863.555      390462.893     2417571.311      390549.558
#Sta/Elev= 26
       0  403.23       4  402.85     7.9  402.24    11.9  401.44    27.7  399.18
    31.7  398.75    43.6   397.8    52.9396.9315    71.3  395.53    79.2     395
    87.1  394.64   95.01394.1199   106.9  393.99   124.4  393.66   130.6  393.56
   139.4  393.68   158.4  393.85   166.3  393.66   197.9  394.04   209.8  394.42
   225.6  395.08   249.4   396.4   257.3  397.14     289  400.37   300.9   401.4
   304.8  401.81
#Mann= 5 ,-1 , 0
       0     .12       0    52.9     .06       0   95.01     .08       0
   124.4    .045       0   139.4     .06       0
Bank Sta=124.4,139.4
XS Rating Curve= 0 ,0
Exp/Cntr=0.3,0.1

Type RM Length L Ch R = 1 ,1858.4  ,95.3,98.3,71.4
XS GIS Cut Line= 3
     2417905.671      390290.427     2417800.419      390279.576
     2417611.617      390265.471
#Sta/Elev= 30
       0  406.28    15.7  404.87    27.4  403.46    31.4  403.16    35.3  402.67
    43.1  401.18      51  400.13    58.8  399.76    62.7  399.08    70.5  397.14
    74.5  396.74    82.3  396.44      94  395.24   101.9   394.9   109.8  394.24
   125.5  393.55   137.4  391.72   141.3  390.67   145.2     390   149.2   389.9
   157.1  390.44     165  391.35   168.9  391.61   180.8  392.07   200.5  393.19
  232.06395.2731   259.6  396.21  268.29396.0939  273.42396.1494   295.1   396.5
#Mann= 6 ,-1 , 0
       0     .12       0   141.3    .045       0   157.1     .12       0
  232.06     .06       0  268.29     .12       0  273.42     .06       0
Bank Sta=141.3,157.1
XS Rating Curve= 0 ,0
Exp/Cntr=0.3,0.1

Type RM Length L Ch R = 1 ,1760.1  ,108.2,117.9,157.5
XS GIS Cut Line= 4
     2417926.504      390238.821     2417825.983      390224.759
     2417812.963      390209.655     2417635.879       390207.05
#Sta/Elev= 30
       0  399.75    15.6  398.17    23.4  396.69    27.3  396.41      39  394.46
    46.8  393.96    62.5  392.34    78.1  391.36    85.9  391.21    93.7  390.73
    97.6  390.14  103.98  388.76   105.5  388.27   109.5  387.84   113.5  388.12
   117.4  388.84   121.4  389.89   141.1  390.88     149  391.48   172.6  394.64
   192.3  396.86   200.2  397.33     208  398.04     212   398.5   223.8  400.51
   227.7  401.01  243.03402.4353   259.2  403.02  284.74 402.845   298.5  402.27
#Mann= 5 ,-1 , 0
       0     .12       0  103.98    .045       0   117.4     .12       0
  243.03     .08       0  284.74     .12       0
Bank Sta=103.98,117.4
XS Rating Curve= 0 ,0
Exp/Cntr=0.3,0.1

Type RM Length L Ch R = 1 ,1642.2  ,220.9,208.8,196
XS GIS Cut Line= 2
     2417976.414      390199.311     2417819.997      390091.787
#Sta/Elev= 30
       0  401.33       4  400.04    15.8  395.56    19.8  394.89    27.7  394.11
    39.5  392.55    47.4  391.95    51.4  391.31    55.4  390.01    59.3  388.33
   61.36  387.81    63.3  387.12    67.2  386.36    71.2  386.16    75.1  386.88
    79.1  387.95      87  389.83    98.9  391.38   102.8  391.75   110.7  392.94
   118.6   393.6   126.5  394.75   130.5  395.72   138.4  397.24   150.3   399.2
   158.2  400.67   166.1  401.86     174  403.68   181.9  406.04   189.8   407.5
#Mann= 3 ,-1 , 0
       0     .12       0   61.36    .045       0    79.1     .12       0
Bank Sta=61.36,79.1
XS Rating Curve= 0 ,0
Exp/Cntr=0.3,0.1

Type RM Length L Ch R = 1 ,1433.4  ,131.2,131.9,131.8
XS GIS Cut Line= 2
     2418041.565      389968.943     2417865.784       389961.13
#Sta/Elev= 28
       0  398.87      20  397.56      24  397.14      32  395.91      36  395.38
      44  394.78      52  393.96      68  391.77      88  389.34      92  388.42
    95.8  387.29    99.1  386.16     100  385.71     104   384.6     108  384.55
     112  385.18     116  386.01     120  387.04     128  389.84     132  391.06
     136     392     144  393.65     148  394.71     156  397.11     160  398.09
     168  399.55     172  400.23     176  400.71
#Mann= 3 ,-1 , 0
       0     .12       0    99.1    .045       0     116     .12       0
Bank Sta=99.1,116
XS Rating Curve= 0 ,0
Exp/Cntr=0.3,0.1

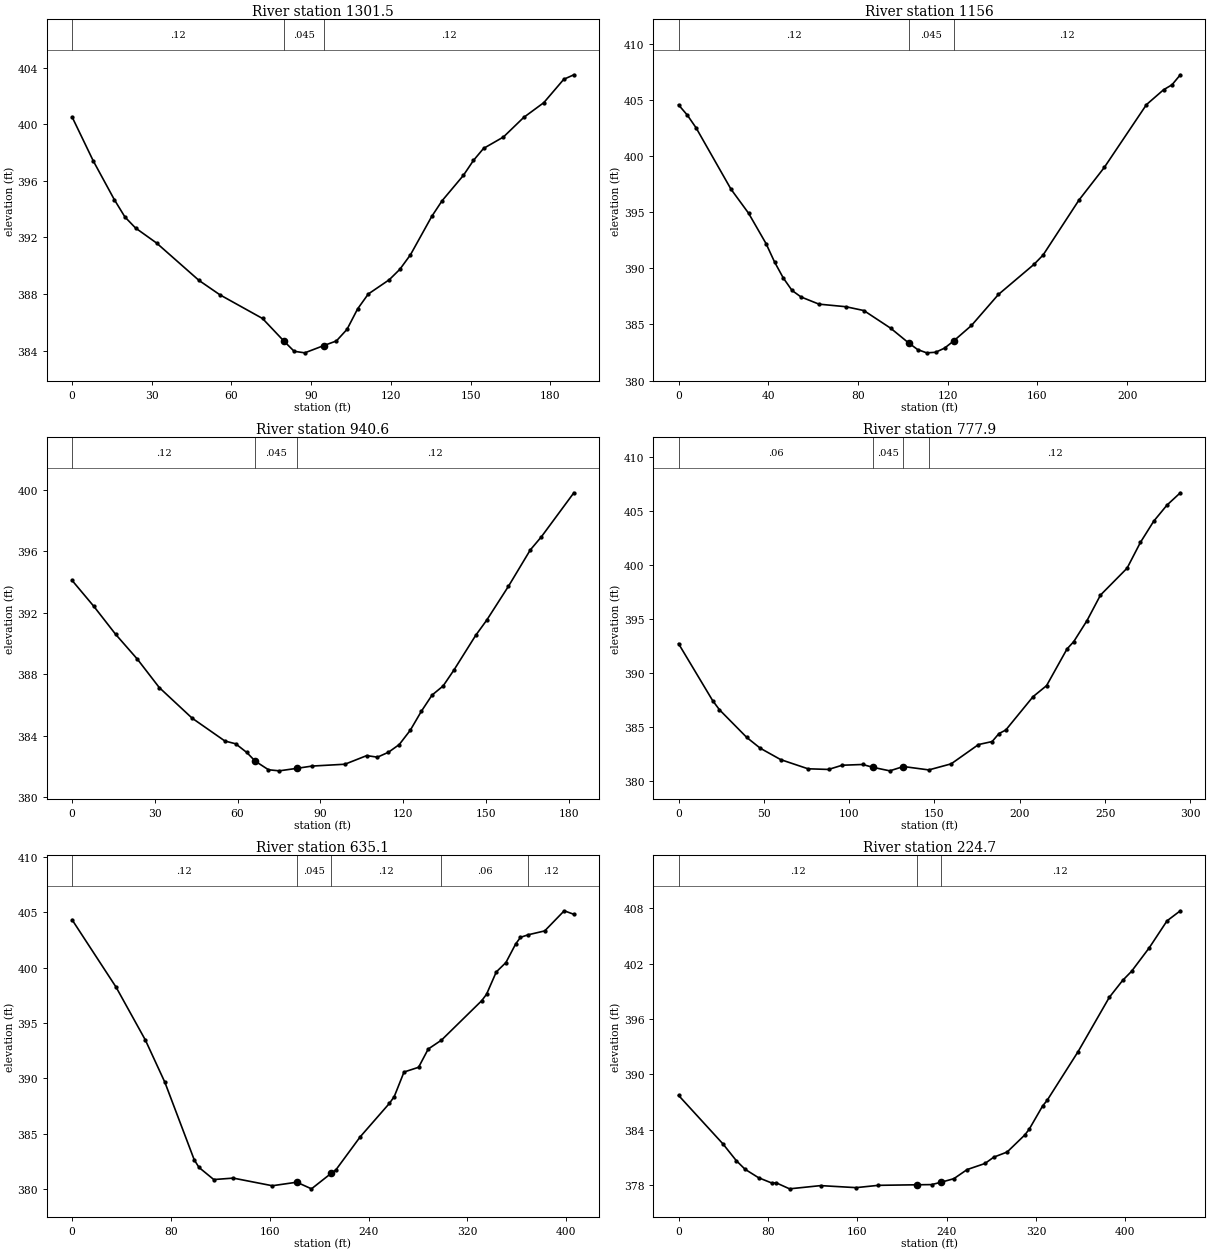
Type RM Length L Ch R = 1 ,1301.5  ,147.5,145.5,143.6
XS GIS Cut Line= 3
     2418037.398      389842.293     2417890.393      389832.918
     2417852.893      389850.974
#Sta/Elev= 30
       0  400.53       8  397.41    15.9  394.68    19.9  393.45    23.9  392.67
    31.8  391.61    47.8  388.96    55.7  387.94    71.7  386.27    79.7  384.68
    83.6  383.95    87.6  383.84    94.7  384.35    99.5  384.68   103.5   385.5
   107.5  386.95   111.5     388   119.4  389.01   123.4  389.75   127.4  390.78
   135.4  393.49   139.3   394.6   147.3  396.39   151.1  397.45   154.9   398.3
   162.4  399.11     170  400.49   177.6  401.54   185.1  403.19   188.9  403.51
#Mann= 3 ,-1 , 0
       0     .12       0    79.7    .045       0    94.7     .12       0
Bank Sta=79.7,94.7
XS Rating Curve= 0 ,0
Exp/Cntr=0.3,0.1

Type RM Length L Ch R = 1 ,1156    ,201.8,215.3,228
XS GIS Cut Line= 4
     2418055.628      389714.689     2418011.351      389690.134
     2417883.502      389693.293     2417849.543      389663.464
#Sta/Elev= 30
       0  404.57     3.9  403.66     7.8  402.53    23.4  397.05    31.2  394.92
      39  392.21    42.8  390.57    46.7  389.14    50.6  388.03    54.6  387.45
    62.6  386.81    74.6  386.58    82.6  386.24    94.6  384.66   102.6  383.35
   106.6  382.76   110.6  382.47   114.6  382.52   118.6  382.89   122.6  383.52
   130.6  384.91   142.6  387.67   158.5  390.36   162.5  391.18   178.5  396.08
   189.8  398.99   208.6  404.59   216.2  405.91     220  406.36   223.7  407.25
#Mann= 3 ,-1 , 0
       0     .12       0   102.6    .045       0   122.6     .12       0
Bank Sta=102.6,122.6
XS Rating Curve= 0 ,0
Exp/Cntr=0.3,0.1

Type RM Length L Ch R = 1 ,940.6   ,160.3,162.8,165.4
XS GIS Cut Line= 2
     2418142.433        389575.8     2417987.051      389481.182
#Sta/Elev= 30
       0  394.12     7.9  392.43    15.8  390.61    23.7  388.99    31.6  387.15
    43.5  385.16    55.4  383.67    59.3  383.49    63.3  382.93    66.4  382.36
    71.2   381.8    75.1  381.73    81.4  381.89      87  382.04    98.9  382.16
   106.8  382.72   110.7  382.62   114.7  382.94   118.6  383.44   122.6  384.37
   126.6   385.6   130.5  386.66   134.5  387.25   138.4  388.28   146.3  390.54
   150.3  391.53   158.2  393.74   166.1   396.1   170.1  396.95   181.9  399.82
#Mann= 3 ,-1 , 0
       0     .12       0    66.4    .045       0    81.4     .12       0
Bank Sta=66.4,81.4
XS Rating Curve= 0 ,0
Exp/Cntr=0.3,0.1

Type RM Length L Ch R = 1 ,777.9   ,137.4,142.8,143.6
XS GIS Cut Line= 3
     2418207.459      389456.748       2418027.9      389316.677
     2417963.084      389302.232
#Sta/Elev= 30
       0  392.71      20  387.42      24  386.57      40     384    47.9     383
    59.9  381.94    75.9  381.09    87.9  381.03    95.9  381.42   107.9  381.49
   114.1  381.22   123.8   380.9   131.8   381.3  146.69 380.985   159.8  381.55
   175.8  383.34   183.8  383.62   187.8  384.36   191.8  384.69   207.8  387.79
   215.7  388.81   227.7  392.22   231.6  392.89   239.4  394.85   247.3  397.22
   262.9  399.72   270.7  402.11   278.5  404.08   286.3  405.58   294.1  406.72
#Mann= 4 ,-1 , 0
       0     .06       0   114.1    .045       0   131.8     .06       0
  146.69     .12       0
Bank Sta=114.1,131.8
XS Rating Curve= 0 ,0
Exp/Cntr=0.3,0.1

Type RM Length L Ch R = 1 ,635.1   ,406.7,410.4,416.8
XS GIS Cut Line= 3
     2418298.032       389406.53     2418147.338      389233.613
     2417970.471      389233.439
#Sta/Elev= 30
       0  404.34    35.6  398.25    59.3  393.47    75.1  389.65    98.9  382.63
   102.8  381.94   114.7  380.85   130.5  380.98   162.1  380.29   181.9  380.61
   193.8  380.01   209.6   381.4   213.6  381.73   233.3  384.72   256.9  387.74
   260.8  388.35   268.7  390.57   280.5     391   288.3  392.65  299.02 393.454
   331.6  397.02   335.5   397.6   343.4  399.62   351.2  400.47   359.1  402.15
     363  402.75  369.31402.9818   382.6  403.33   398.4  405.15   406.2  404.83
#Mann= 5 ,-1 , 0
       0     .12       0   181.9    .045       0   209.6     .12       0
  299.02     .06       0  369.31     .12       0
Bank Sta=181.9,209.6
XS Rating Curve= 0 ,0
Exp/Cntr=0.3,0.1

Type RM Length L Ch R = 1 ,224.7   ,184,190,196.2
XS GIS Cut Line= 2
     2418648.857      389357.137     2418405.367      388979.533
#Sta/Elev= 30
       0  387.73    39.8  382.46    51.7  380.65    59.6  379.71    71.6   378.8
    83.5  378.22    87.5  378.24    99.4  377.59   127.2  377.94     159  377.72
   178.9  377.97   213.2  378.03   226.6  378.05   234.6  378.29   246.5  378.69
   258.4  379.68   274.4  380.34   282.3  381.03   294.2  381.58   310.1  383.44
   314.1  384.08     326  386.58     330  387.18   357.8  392.48   385.7  398.36
   397.6  400.19   405.6  401.18   421.5  403.74   437.4  406.66   449.3  407.75
#Mann= 3 ,-1 , 0
       0     .12       0   213.2    .045       0   234.6     .12       0
Bank Sta=213.2,234.6
XS Rating Curve= 0 ,0
Exp/Cntr=0.3,0.1

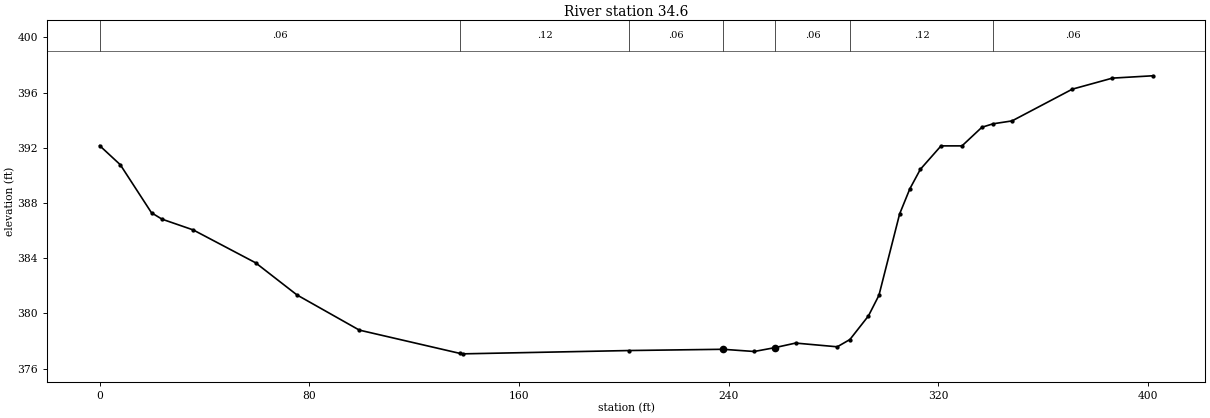
Type RM Length L Ch R = 1 ,34.6    ,27.5,34.6,41.8
XS GIS Cut Line= 3
     2418798.596      389387.085     2418687.919      389077.189
     2418720.471      389012.085
#Sta/Elev= 30
       0  392.16     7.9  390.77    19.8  387.29    23.8  386.83    35.7  386.05
    59.5  383.67    75.3  381.34    99.1  378.79   137.6 377.097   138.8  377.07
   202.2  377.31   237.9   377.4   249.8  377.24   257.7  377.52   265.6  377.85
   281.5  377.58  286.32378.1071   293.4  379.82   297.4  381.31   305.3  387.21
   309.2  389.03   313.2  390.44   321.1  392.14   329.1  392.14   336.7  393.49
  340.96  393.74   348.2  393.95   371.2  396.25   386.5  397.05   401.9  397.22
#Mann= 7 ,-1 , 0
       0     .06       0   137.6     .12       0   202.2     .06       0
   237.9    .045       0   257.7     .06       0  286.32     .12       0
  340.96     .06       0
Bank Sta=237.9,257.7
XS Rating Curve= 0 ,0
Exp/Cntr=0.3,0.1

Chan Stop Cuts=-1
Use User Specified Reach Order=0
Composite Channel Slope=5